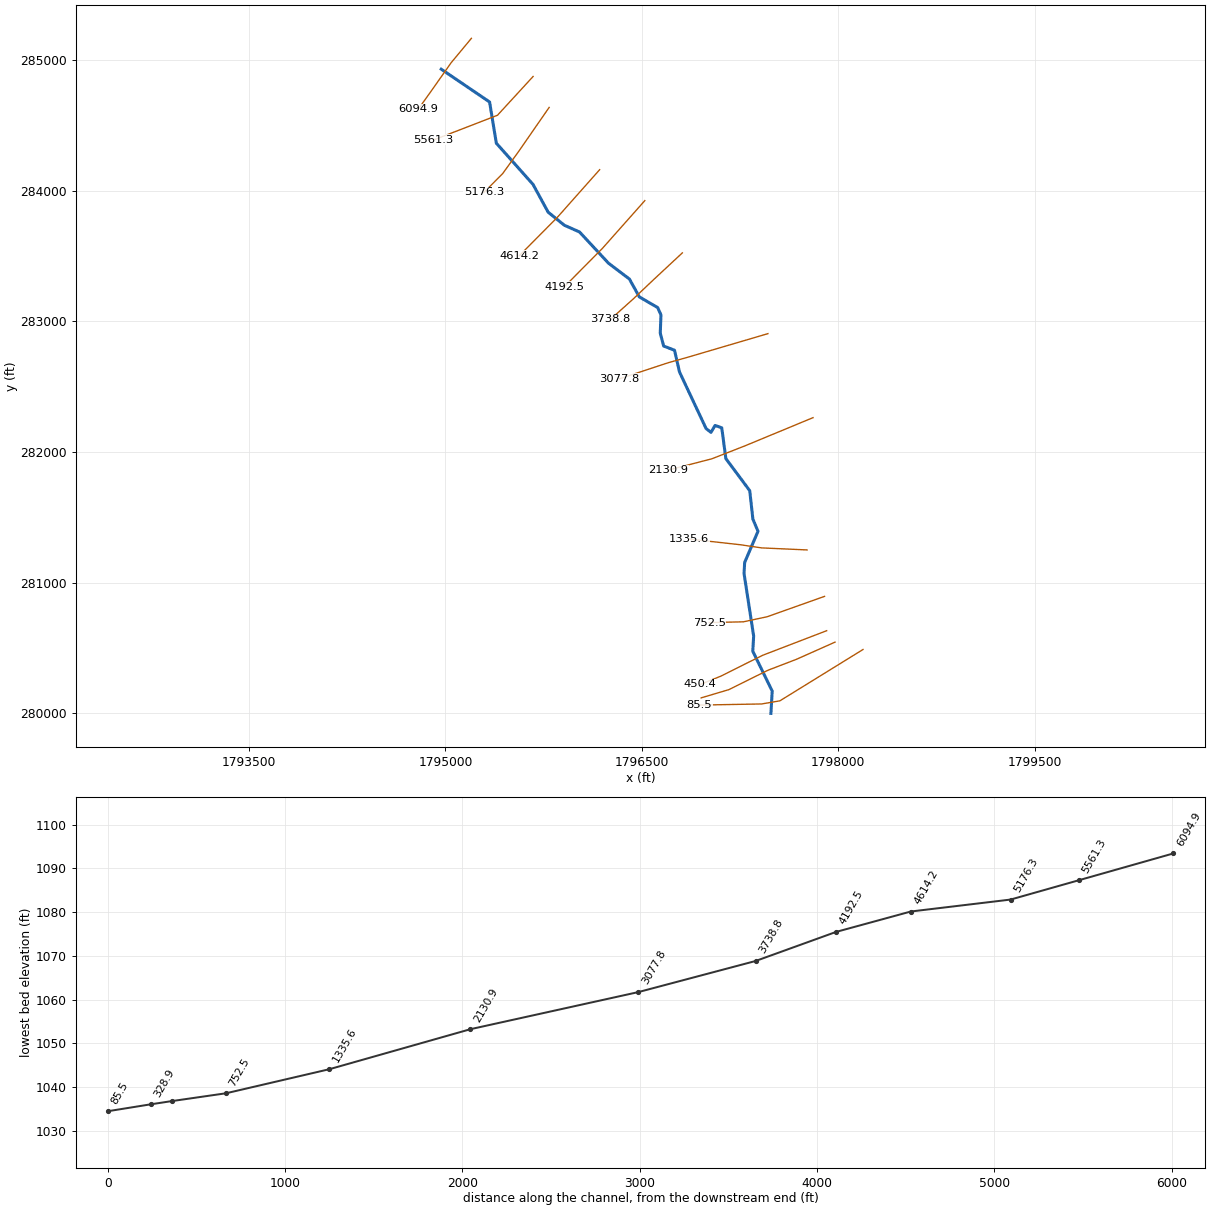
--- BuckRun.prj (project) ---

Proj Title=BuckRun
Current Plan=p01
Default Exp/Contr=0,0
English Units
Geom File=g01
Flow File=f01
Plan File=p01
BEGIN DESCRIPTION:
END DESCRIPTION:
DSS Export Rating Curves= 0
DSS Export Rating Curve Sorted= 0
DSS Export Volume Flow Curves= 0
DXF OffsetX= 0
DXF OffsetY= 0
DXF ScaleX= 0
DXF ScaleY= 0

--- BuckRun.p01 (plan) ---

Plan Title=Floodplain
Program Version=4.00
Geom File=g01
Flow File=f01
K Sum by GR=0
Std Step Tol=0.01
Critical Tol=0.01
Num of Std Step Trials=20
Max Error Tol=0.3
Flow Tol Ratio=0.001
Split Flow NTrial=30
Split Flow Tol=0.02
Split Flow Ratio=0.02
Log Output Level=0
Friction Slope Method=1
Unsteady Friction Slope Method=2
Unsteady Bridges Friction Slope Method=1
Global Log Level=0
CheckData=False
Run HTab=0
Run UNet=0
Run PostProcess=0
UNET Theta=0
UNET Theta Warmup=0
UNET ZTol=0
UNET ZSATol=0
UNET MxIter=0
UNET MaxInSteps=0
UNET DtIC=0
UNET DtMin=0
UNET MaxCRTS=0
UNET WFStab=0
UNET SFStab=0
UNET WFX=0
UNET SFX=0
UNET DSS MLevel=0
UNET DZMax Abort=0
UNET Convert EG Bridges=0
UNET Use Existing IB Tables=0
UNET Froude Limit=0
UNET Froude Power=0
Write IC File=0
Echo Input=False
Echo Output=False
Write Detailed=0

--- BuckRun.f01 (steady flow) ---

Flow Title=NFF Regression Equation
Program Version=4.10
Number of Profiles= 1
Profile Names=P100yr
River Rch & RM=BuckRun,Main            ,6094.9
     993
River Rch & RM=BuckRun,Main            ,4614.2
    1036
River Rch & RM=BuckRun,Main            ,85.5
    1148
Boundary for River Rch & Prof#=BuckRun,Main            , 1
Up Type= 0
Dn Type= 3
Dn Slope=0.00653
DSS Import GetInterval= 0
DSS Import GetPeak= 0
DSS Import FillOption= 0

--- BuckRun.g01 (geometry) ---

Geom Title=USGS 10m DEM
Program Version=4.10

River Reach=BuckRun         ,Main
Reach XY= 30
      1794967.93         284929.     1795337.179      284677.965
     1795388.641      284362.631      1795668.85      284047.185
      1795784.25      283834.772     1795907.618      283735.119
     1796023.989      283683.267     1796244.162      283445.355
     1796405.228      283322.645     1796480.802      283186.315
     1796620.408      283104.969     1796645.782       283048.52
     1796640.339      282909.063     1796666.312      282810.451
     1796749.285       282778.33     1796787.274      282612.078
     1796990.245      282179.163     1797027.452      282149.835
      1797058.75      282202.723     1797109.998      282184.842
     1797141.147      281949.348     1797323.554       281703.63
     1797347.683      281485.803     1797386.778      281393.261
      1797284.79      281154.251     1797280.152       281069.81
     1797353.507      280591.493     1797346.968      280475.012
     1797495.193      280169.905     1797485.359      279999.551

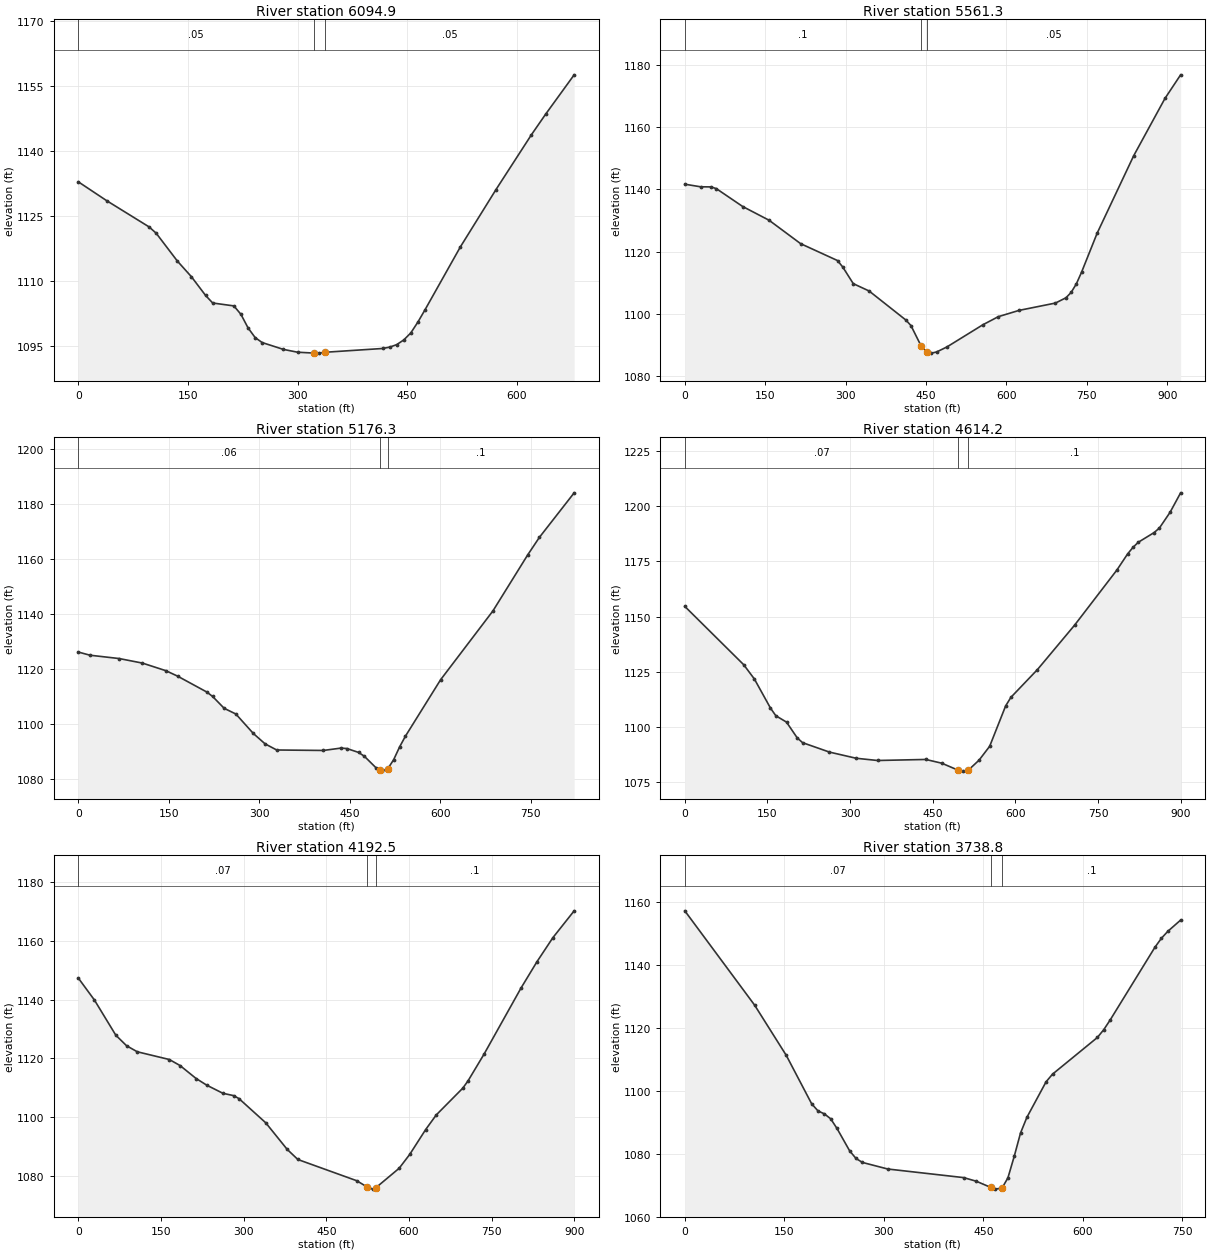
Type RM Length L Ch R = 1 ,6094.9  ,546.7,533.6,519.6
XS GIS Cut Line= 4
     1795198.247      285165.067     1795043.823      284978.811
     1794893.586      284764.783     1794791.997      284622.098
#Sta/Elev= 30
       0 1132.96    38.7 1128.62    96.8 1122.56   106.5 1121.11   135.5 1114.68
   154.8 1111.05   174.2 1106.73   183.9 1104.99   212.9 1104.32   222.6 1102.36
   232.3 1099.24     242 1097.01   251.6 1095.86   280.7 1094.28   300.1 1093.63
   322.7 1093.43   329.1 1093.42   337.7 1093.62   416.3 1094.49     426  1094.8
   435.6 1095.37   445.3 1096.45     455 1098.08   464.7 1100.58   474.4  1103.4
   522.9 1117.95   571.6 1131.17   620.2 1143.85   639.7 1148.61   678.6 1157.66
#Mann= 3 , 0 , 0
       0     .05       0   322.7    .045       0   337.7     .05       0
Bank Sta=322.7,337.7
XS Rating Curve= 0 ,0
Exp/Cntr=0.3,0.1

Type RM Length L Ch R = 1 ,5561.3  ,372,385,398.4
XS GIS Cut Line= 4
     1795669.601        284873.4     1795397.466      284576.525
     1795209.966      284503.609     1794910.486      284387.723
#Sta/Elev= 30
       0  1141.7    29.5 1140.86    49.1 1140.83    58.9 1140.26     108 1134.51
   157.2 1130.09   216.1 1122.54   284.9  1117.1   294.7 1115.01   314.3 1109.66
   343.8  1107.3   412.3 1097.96   421.9 1096.16     441 1089.54   452.2 1087.52
   460.2 1087.28   469.8 1087.65     489 1089.27     556 1096.41   584.8 1099.02
   623.4 1101.04   691.5 1103.41     711  1105.1   720.7 1106.82   730.4 1109.57
   740.1 1113.31   769.3 1125.93   837.4 1150.85   895.8 1169.33     925 1176.93
#Mann= 3 , 0 , 0
       0      .1       0     441    .045       0   452.2     .05       0
Bank Sta=441,452.2
XS Rating Curve= 0 ,0
Exp/Cntr=0.3,0.1

Type RM Length L Ch R = 1 ,5176.3  ,565.4,562.2,558.3
XS GIS Cut Line= 4
     1795791.997      284636.421     1795560.877      284302.075
     1795435.877      284128.464     1795293.299       283985.38
#Sta/Elev= 30
       0 1126.18    19.4 1125.03    67.7 1123.82   106.4 1122.16   145.2  1119.4
   164.5 1117.43   212.9 1111.66   222.6 1110.05   241.9 1105.71   261.3 1103.64
   290.3 1096.55   309.7 1092.79     329 1090.55   406.4 1090.38   435.6 1091.24
   445.4 1091.08   464.8 1089.67   474.5 1088.25     494 1084.02     500  1083.3
   503.7 1082.86   513.4 1083.76   523.1 1087.05   532.9 1091.68   542.6  1095.6
   600.9 1116.12   687.7 1141.16   745.4 1161.55   764.7  1167.9   822.4 1184.11
#Mann= 3 , 0 , 0
       0     .06       0     500    .045       0   513.4      .1       0
Bank Sta=500,513.4
XS Rating Curve= 0 ,0
Exp/Cntr=0.3,0.1

Type RM Length L Ch R = 1 ,4614.2  ,422,421.7,421.7
XS GIS Cut Line= 3
     1796177.414      284159.859     1795855.313      283796.073
     1795564.166      283501.848
#Sta/Elev= 30
       0 1154.66   106.9 1128.27   126.3  1121.8   155.5 1108.65   165.2 1105.19
   184.6  1102.3   204.1 1095.14   213.8    1093   262.4 1088.75     311 1085.95
   349.8 1084.94   437.3 1085.41   466.4 1083.71   495.5 1080.61   505.1 1080.13
   514.8 1080.64     534 1085.08   553.3 1091.39   582.2  1109.6   591.8 1113.51
   639.9 1126.05   707.3 1146.14   784.3 1171.16   803.6 1178.39   813.2 1181.31
   822.8 1183.64   851.7 1188.05   861.3 1190.11   880.6  1197.2   899.8 1206.03
#Mann= 3 , 0 , 0
       0     .07       0   495.5    .045       0   514.8      .1       0
Bank Sta=495.5,514.8
XS Rating Curve= 0 ,0
Exp/Cntr=0.3,0.1

Type RM Length L Ch R = 1 ,4192.5  ,454.2,453.7,453.1
XS GIS Cut Line= 3
     1796522.466      283923.314     1796200.365      283559.527
     1795909.218      283265.303
#Sta/Elev= 30
       0 1147.32    29.2 1139.85      68 1127.88    87.5 1124.29   106.9 1122.23
   165.2 1119.59   184.6 1117.54   213.8 1113.12   233.2 1110.84   262.4 1108.09
   281.8  1107.3   291.5 1106.29   340.1 1098.05     379    1089   398.4 1085.55
   505.1 1078.33   524.4 1076.16     534 1075.46   540.1 1075.96   582.2 1082.56
   601.4 1087.28   630.3 1095.74   649.5 1100.71   697.7 1109.84   707.3 1112.35
   736.2  1121.4   803.6 1144.01   832.4 1152.92   861.3 1161.11   899.8 1170.22
#Mann= 3 , 0 , 0
       0     .07       0   524.4    .045       0   540.1      .1       0
Bank Sta=524.4,540.1
XS Rating Curve= 0 ,0
Exp/Cntr=0.3,0.1

Type RM Length L Ch R = 1 ,3738.8  ,672.2,661,648.3
XS GIS Cut Line= 4
     1796808.924       283523.14     1796592.161      283321.032
     1796433.307      283169.991     1796260.747      283015.327
#Sta/Elev= 30
       0 1157.22   105.2 1127.27     153 1111.28   191.2 1095.92   200.8 1093.65
   210.3 1092.73   219.9 1091.15   229.4 1088.08   248.6 1080.92   258.1 1078.54
   267.7 1077.29   305.9  1075.2   420.3 1072.47   439.3 1071.32   461.2 1069.35
   467.9 1068.81  478.17 1069.16     487 1072.39   496.5 1079.22     506 1086.63
   515.6 1091.62   544.5  1102.9   554.2 1105.33   621.8 1116.98   631.4 1119.45
   641.1 1122.54   708.7 1145.69   718.3 1148.49     728 1150.71   747.3 1154.28
#Mann= 3 , 0 , 0
       0     .07       0   461.2    .045       0  478.17      .1       0
Bank Sta=461.2,478.17
XS Rating Curve= 0 ,0
Exp/Cntr=0.3,0.1

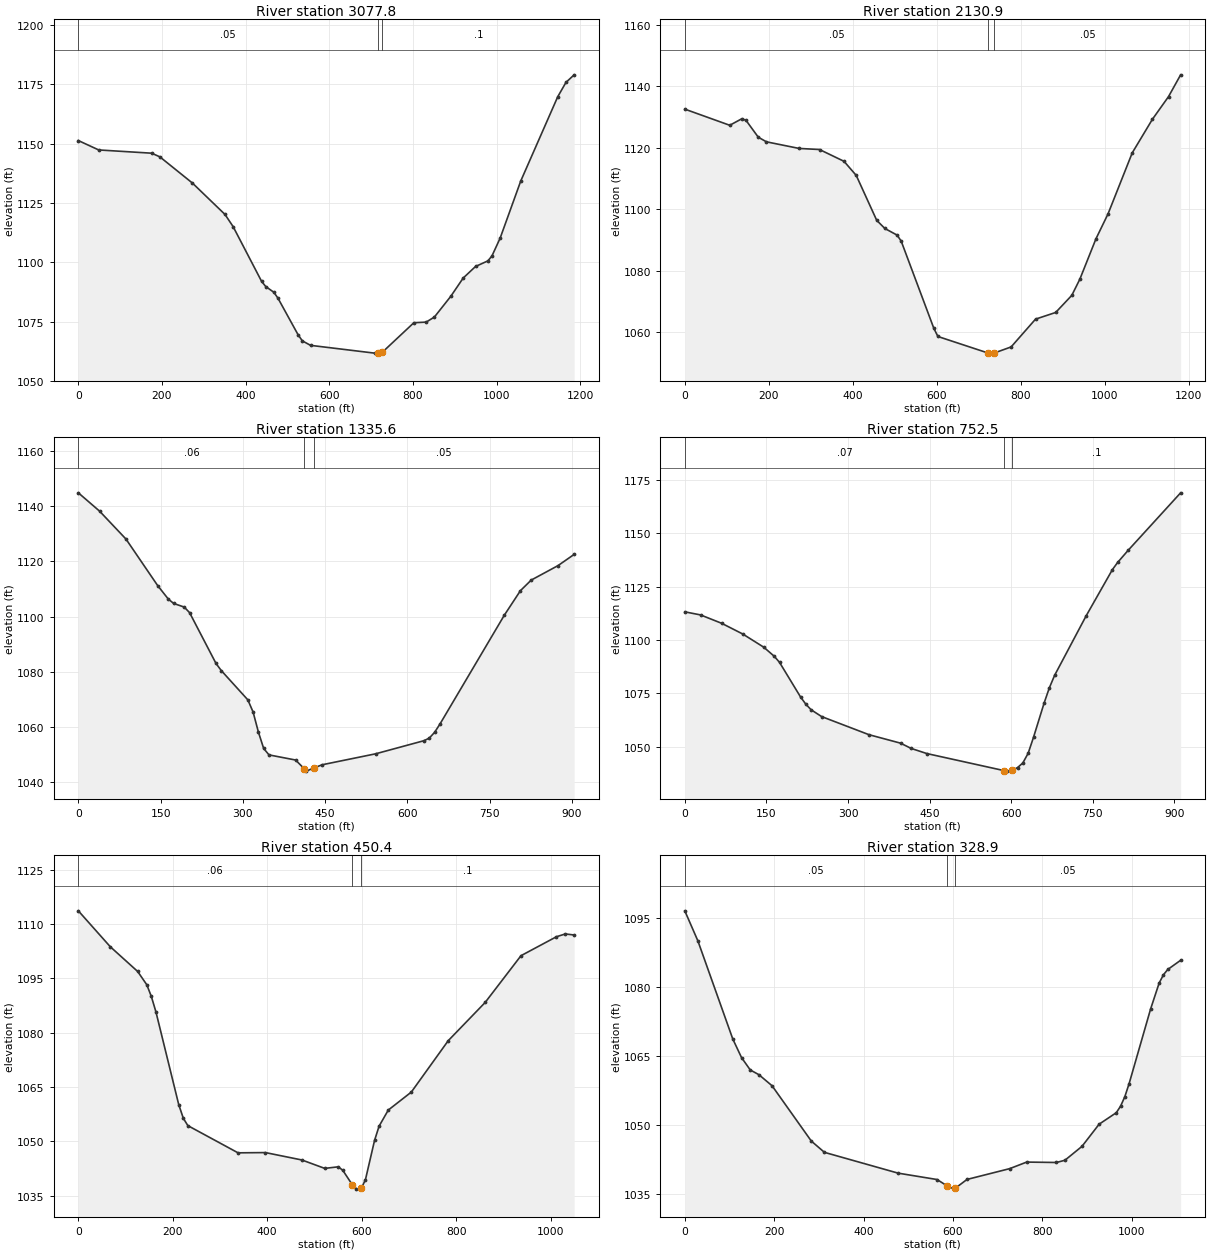
Type RM Length L Ch R = 1 ,3077.8  ,940.4,946.9,948.9
XS GIS Cut Line= 4
     1797462.604      282905.321     1796846.162      282723.464
     1796702.187      282683.098     1796328.923      282559.834
#Sta/Elev= 30
       0 1151.35    48.7 1147.39   175.3 1146.02   194.8 1144.49   272.7 1133.43
   350.6 1120.19     370 1115.06   438.2 1091.94     448 1089.79   467.4 1087.36
   477.2 1084.88   525.8  1069.3   535.6 1066.86   555.1 1064.98   708.1  1061.7
   716.9  1061.7   726.8 1062.09   802.1 1074.52   831.5 1074.78   851.2 1076.92
   890.5 1085.69     920 1093.36   949.5 1098.24     979  1100.6   988.8 1102.69
  1008.4 1110.22  1057.6 1134.28    1146 1169.81  1165.7 1175.88  1185.3 1179.07
#Mann= 3 , 0 , 0
       0     .05       0   716.9    .045       0   726.8      .1       0
Bank Sta=716.9,726.8
XS Rating Curve= 0 ,0
Exp/Cntr=0.3,0.1

Type RM Length L Ch R = 1 ,2130.9  ,806.6,795.3,782.9
XS GIS Cut Line= 4
     1797807.005      282262.439     1797286.172      282046.293
     1797033.567      281947.334     1796699.149      281860.674
#Sta/Elev= 30
       0 1132.53     107 1127.28   136.1 1129.42   145.8 1128.88     175  1123.4
   194.4  1121.9   272.2 1119.75   320.8  1119.4   379.2 1115.56   408.3 1110.97
     457 1096.38   476.4 1093.73   505.6 1091.57   515.3 1089.62     593 1061.28
   602.7 1058.62   722.2 1053.24   728.6 1053.21   737.2 1053.26   777.1 1055.23
   835.2 1064.26   883.2 1066.43   921.6    1072   940.8 1077.27   979.1 1090.38
  1007.9 1098.49  1065.5 1118.32  1113.5 1129.23  1151.9  1136.6  1180.7 1143.68
#Mann= 3 , 0 , 0
       0     .05       0   722.2    .045       0   737.2     .05       0
Bank Sta=722.2,737.2
XS Rating Curve= 0 ,0
Exp/Cntr=0.3,0.1

Type RM Length L Ch R = 1 ,1335.6  ,574.7,583.1,590.6
XS GIS Cut Line= 4
     1797761.281      281250.223     1797414.059      281265.848
     1797250.864      281290.154     1796861.975      281333.557
#Sta/Elev= 30
       0 1144.87    38.6 1138.26    86.9 1128.11   144.8 1111.22   164.1 1106.37
   173.8  1104.8   193.1 1103.48   202.8 1101.47     251 1083.06   260.7 1080.46
     309 1069.88   318.6 1065.47   328.3 1058.18   337.9 1052.26   347.6 1049.94
   396.1 1048.08   412.3 1044.83   415.5 1044.06   429.3  1045.2   444.6 1046.37
   541.9 1050.33     630 1055.08   639.7 1056.01   649.5 1058.11   659.3 1061.13
   776.7 1100.58     806 1109.44   825.6 1113.26   874.5 1118.51   903.9 1122.57
#Mann= 3 , 0 , 0
       0     .06       0   412.3    .045       0   429.3     .05       0
Bank Sta=412.3,429.3
XS Rating Curve= 0 ,0
Exp/Cntr=0.3,0.1

Type RM Length L Ch R = 1 ,752.5   ,296.7,302.1,307.7
XS GIS Cut Line= 4
     1797894.895      280894.904      1797457.47      280739.199
     1797275.178      280700.136     1797014.687      280694.383
#Sta/Elev= 30
       0 1113.25      29  1111.8    67.7 1107.88   106.4 1102.87   145.1 1096.67
   164.4 1092.41   174.1 1089.56   212.8  1073.3   222.5 1069.92   232.2 1067.32
   251.5 1064.13   338.6 1055.63   396.6 1051.66     416  1049.2     445 1046.78
   587.3 1038.76   591.9 1038.55   601.7 1038.93   611.5  1040.2   621.3 1042.38
   631.1 1046.94   640.9 1054.39   660.4 1070.47     670  1077.6   679.7 1083.47
   737.6 1111.34   785.8    1133   795.5  1136.4   814.8 1142.08   911.3 1169.06
#Mann= 3 , 0 , 0
       0     .07       0   587.3    .045       0   601.7      .1       0
Bank Sta=587.3,601.7
XS Rating Curve= 0 ,0
Exp/Cntr=0.3,0.1

Type RM Length L Ch R = 1 ,450.4   ,121.5,121.5,121.5
XS GIS Cut Line= 5
     1797911.172       280632.23     1797424.192       280444.73
     1797321.154      280393.819     1797102.892      280284.307
      1796946.12      280221.328
#Sta/Elev= 30
       0 1113.69    67.6 1103.77   125.6 1096.94     145 1093.25   154.6 1090.02
   164.3 1085.77   212.6 1060.13   222.3 1056.36   231.9 1054.33   338.2 1046.81
   396.2 1046.88   473.5 1044.83   521.8 1042.51   550.6 1042.95   560.1 1041.96
   579.8 1038.05   588.9 1036.83   598.4 1036.78  599.54 1037.05     608 1039.42
   627.2 1050.22   636.8 1054.17   656.3 1058.63   705.1  1063.6   783.3 1077.81
   861.4 1088.36   937.3 1101.29  1012.4 1106.53  1031.1  1107.3  1049.9 1107.01
#Mann= 3 , 0 , 0
       0     .06       0   579.8    .045       0  599.54      .1       0
Bank Sta=579.8,599.54
XS Rating Curve= 0 ,0
Exp/Cntr=0.3,0.1

Type RM Length L Ch R = 1 ,328.9   ,249.3,243.4,236.5
XS GIS Cut Line= 6
     1797974.766      280544.679     1797680.477      280413.349
     1797463.255      280329.713     1797360.217      280278.801
     1797164.219       280181.18     1796952.631      280118.246
#Sta/Elev= 30
       0 1096.63    29.3 1090.08   107.4 1068.72     127 1064.67   146.5 1061.98
     166 1060.94   195.3 1058.54   283.2 1046.49   312.5 1044.04   477.4 1039.51
   564.6 1038.12  586.67 1036.76   602.9 1036.03   604.6 1036.17   631.6 1038.14
   727.1 1040.49   765.2 1041.92   831.8 1041.83   850.8 1042.32   888.9 1045.34
   927.3 1050.17   965.7 1052.67   975.3 1054.09   984.9 1056.17   994.5 1059.03
  1042.5 1075.25  1061.7 1080.92  1071.3 1082.71  1080.9 1083.86  1109.7 1085.86
#Mann= 3 , 0 , 0
       0     .05       0  586.67    .045       0   604.6     .05       0
Bank Sta=586.67,604.6
XS Rating Curve= 0 ,0
Exp/Cntr=0.3,0.1

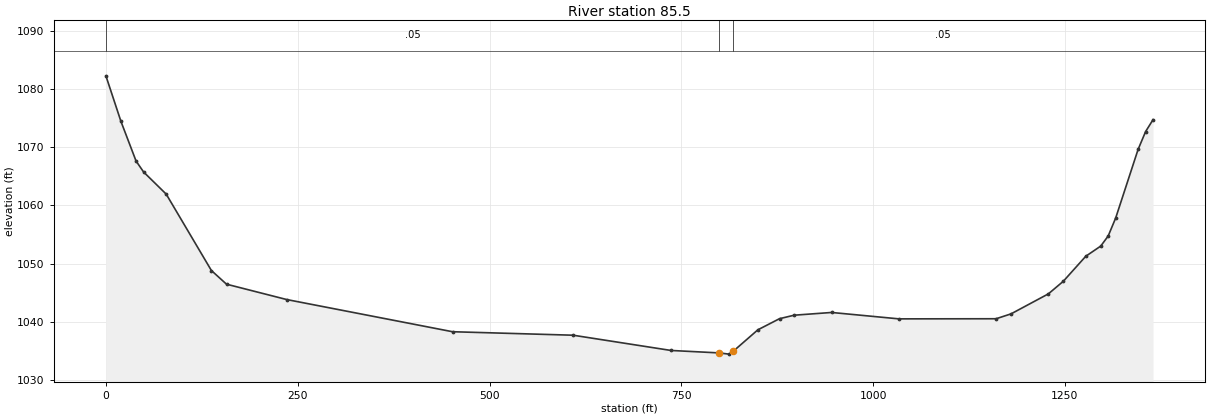
Type RM Length L Ch R = 1 ,85.5    ,91.7,85.5,79.9
XS GIS Cut Line= 4
     1798188.572      280488.325     1797553.806       280095.53
     1797414.917      280071.659     1796937.487      280062.978
#Sta/Elev= 30
       0 1082.27    19.6 1074.44    39.3 1067.63    49.1 1065.75    78.6 1061.94
   137.5 1048.81   157.2 1046.46   235.7 1043.82   451.8 1038.29     609 1037.69
   736.6 1035.07  799.06 1034.65   812.2 1034.44   817.4  1034.9   849.8 1038.62
     878 1040.53   897.1 1041.13   945.9  1041.6  1033.6  1040.5  1160.3 1040.52
  1179.8 1041.36  1228.5  1044.8    1248 1046.97  1277.2 1051.26  1296.7 1053.01
  1306.4 1054.74  1316.2 1057.84  1345.4 1069.62  1355.2 1072.69  1364.9 1074.74
#Mann= 3 , 0 , 0
       0     .05       0  799.06    .045       0   817.4     .05       0
Bank Sta=799.06,817.4
XS Rating Curve= 0 ,0
Exp/Cntr=0.3,0.1

Chan Stop Cuts=-1
Use User Specified Reach Order=0
Composite Channel Slope=5